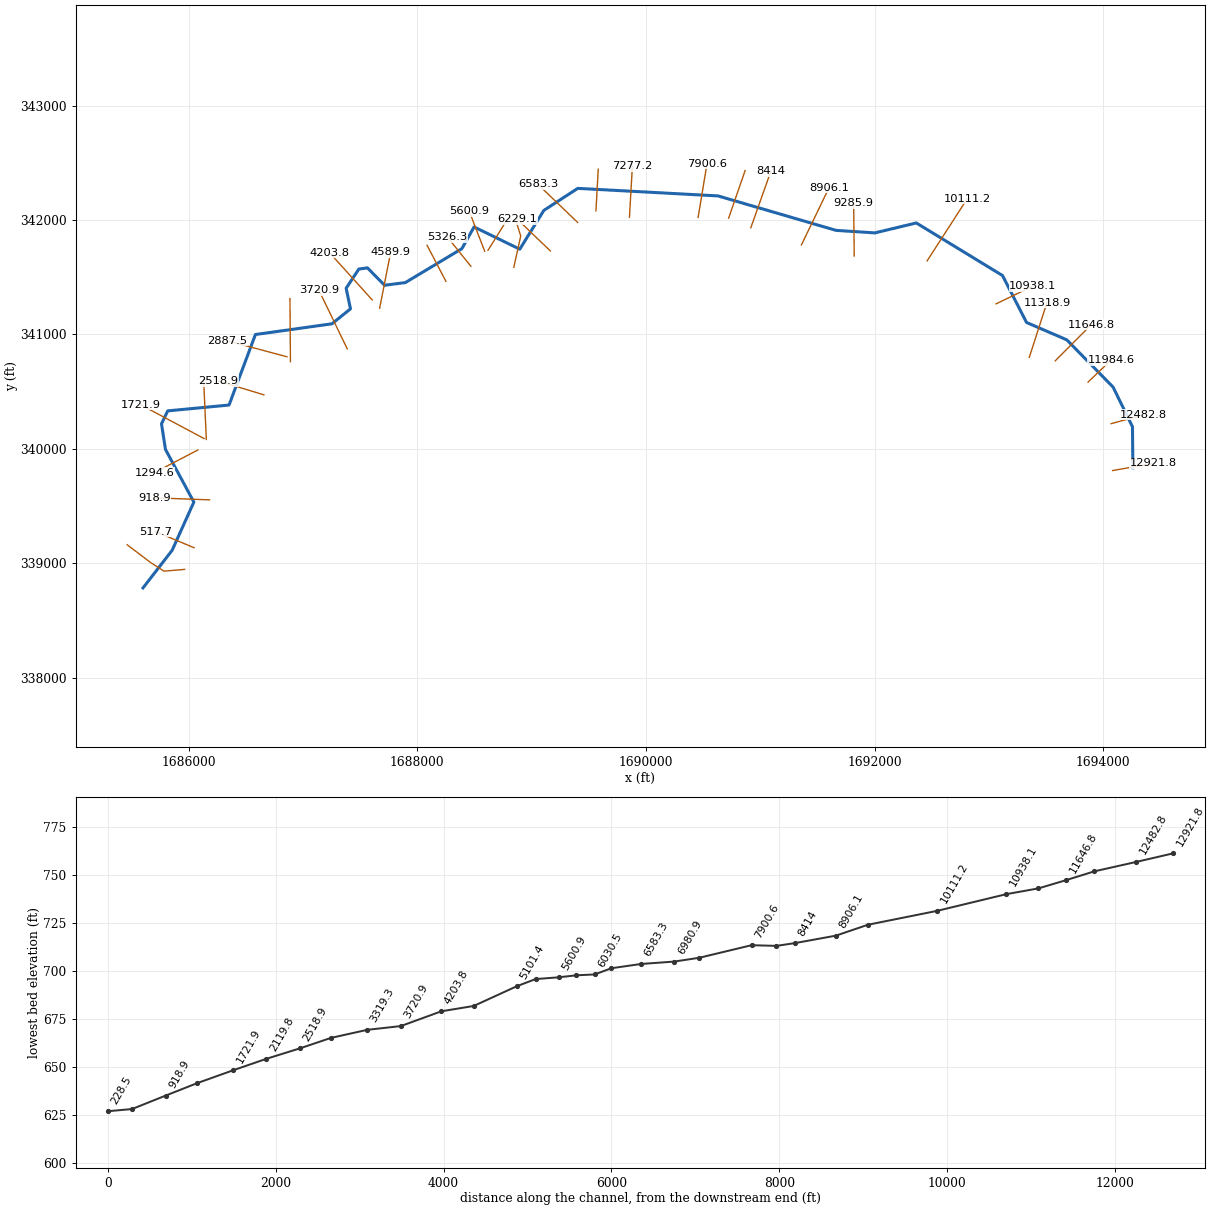
--- MILLCRK.prj (project) ---

Proj Title=MILLCRK
Current Plan=p01
Default Exp/Contr=0,0
English Units
Geom File=g01
Flow File=f01
Plan File=p01
BEGIN DESCRIPTION:
END DESCRIPTION:
DSS Export Rating Curves= 0
DSS Export Rating Curve Sorted= 0
DSS Export Volume Flow Curves= 0
DXF Filename=C:\MILLCRK.
DXF OffsetX= 0
DXF OffsetY= 0
DXF ScaleX= 0
DXF ScaleY= 0

--- MILLCRK.p01 (plan) ---

Plan Title=Floodplain
Program Version=4.00
Geom File=g01
Flow File=f01
K Sum by GR=0
Std Step Tol=0.01
Critical Tol=0.01
Num of Std Step Trials=20
Max Error Tol=0.3
Flow Tol Ratio=0.001
Split Flow NTrial=30
Split Flow Tol=0.02
Split Flow Ratio=0.02
Log Output Level=0
Friction Slope Method=1
Unsteady Friction Slope Method=2
Unsteady Bridges Friction Slope Method=1
Global Log Level=0
CheckData=False
Run HTab=0
Run UNet=0
Run PostProcess=0
UNET Theta=0
UNET Theta Warmup=0
UNET ZTol=0
UNET ZSATol=0
UNET MxIter=0
UNET MaxInSteps=0
UNET DtIC=0
UNET DtMin=0
UNET MaxCRTS=0
UNET WFStab=0
UNET SFStab=0
UNET WFX=0
UNET SFX=0
UNET DSS MLevel=0
UNET DZMax Abort=0
UNET Convert EG Bridges=0
UNET Use Existing IB Tables=0
UNET Froude Limit=0
UNET Froude Power=0
Write IC File=0
Echo Input=False
Echo Output=False
Write Detailed=0

--- MILLCRK.f01 (steady flow) ---

Flow Title=NFF Regression Equation
Program Version=4.00
Number of Profiles=1
Profile Names=P100yr
River Rch & RM=MILLCRK,Main      ,12921.8
1120.271
River Rch & RM=MILLCRK,Main      ,11984.6
1130.957
River Rch & RM=MILLCRK,Main      ,11318.9
1255.626
River Rch & RM=MILLCRK,Main      ,9285.9
1474.687
River Rch & RM=MILLCRK,Main      ,9285.9
1288.360
River Rch & RM=MILLCRK,Main      ,7900.6
1551.096
River Rch & RM=MILLCRK,Main      ,5600.9
1683.376
River Rch & RM=MILLCRK,Main      ,4589.9
1806.556
River Rch & RM=MILLCRK,Main      ,228.5
1890.617
Boundary for River Rch & Prof#=MILLCRK,Main      ,1
Up Type=0
Dn Type=3
Dn Slope=0.01383

--- MILLCRK.g01 (geometry) ---

Geom Title=USGS 10m DEM
Program Version=4.10

River Reach=MILLCRK         ,Main
Reach XY= 30
     1694258.202      339835.378     1694254.726      340193.339
     1694085.593      340539.716     1693680.135      340953.283
     1693327.967       341105.04     1693118.287      341515.131
     1692364.136      341975.035     1692001.541      341888.151
     1691662.116      341910.162     1690629.937      342211.359
     1689403.138      342277.391     1689106.575      342085.088
     1688895.737      341745.662     1688496.072      341940.282
     1688389.495      341750.296     1687894.837      341453.733
      1687712.96      341430.564      1687563.52      341582.321
     1687488.221      341571.895      1687377.01       341403.92
     1687415.238       341224.36     1687253.055      341093.455
     1686583.471       340999.62      1686352.94      340383.325
     1685816.577      340332.353      1685762.13      340218.825
     1685796.884      339995.245     1686045.121      339535.153
     1685855.176      339113.567     1685600.371      338784.637

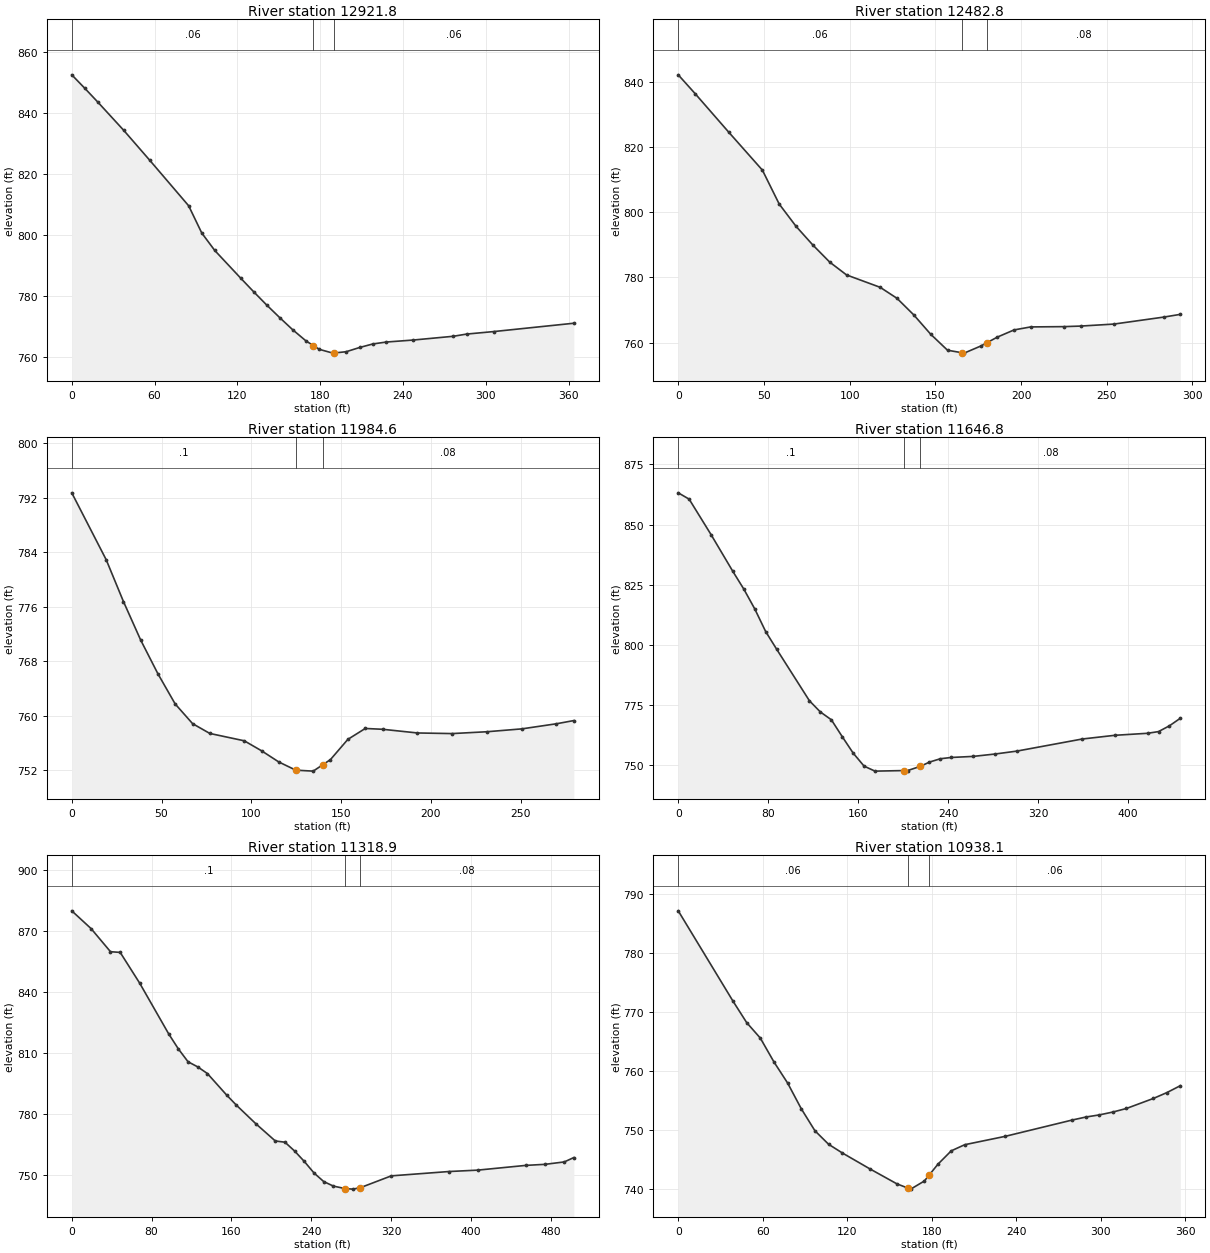
Type RM Length L Ch R = 1 ,12921.8 ,438.3,439,439.7
XS GIS Cut Line= 3
     1694080.995      339810.806     1694238.698      339838.123
     1694439.405      339872.888
#Sta/Elev= 27
       0  852.47     9.4  848.08    18.8  843.57    37.7  834.25    56.5  824.46
    84.7  809.54    94.2  800.61   103.6   794.9   122.4  785.82   131.8  781.36
   141.2  777.03   150.6  772.91     160  768.94   169.8  765.21     175  763.73
   179.4  762.48   189.2  761.24     190  761.28   198.8   761.7   208.6  763.09
   218.2  764.25     228  764.88   247.4  765.53   276.4  766.76   286.2  767.49
   305.6   768.3   363.8  771.04
#Mann= 3 , 0 , 0
       0     .06       0     175    .045       0     190     .06       0
Bank Sta=175,190
XS Rating Curve= 0 ,0
Exp/Cntr=0.3,0.1

Type RM Length L Ch R = 1 ,12482.8 ,486.8,498.1,509.4
XS GIS Cut Line= 3
     1694068.184      340220.603     1694219.795      340261.667
      1694350.87      340297.169
#Sta/Elev= 26
       0  842.08     9.8  836.35    29.4  824.54    49.1  812.87    58.9  802.48
    68.7  795.67    78.5  789.94    88.4  784.67    98.2  780.75   117.8  776.96
   127.6   773.6   137.4  768.51   147.3  762.57   157.1  757.68   165.3  756.93
   166.8  756.79   176.5  758.97   180.3  760.04   186.2  761.71   195.9   763.9
   205.6  764.82     225  764.91   234.7  765.08   254.1  765.69   283.2  767.83
   292.9  768.67
#Mann= 3 , 0 , 0
       0     .06       0   165.3    .045       0   180.3     .08       0
Bank Sta=165.3,180.3
XS Rating Curve= 0 ,0
Exp/Cntr=0.3,0.1

Type RM Length L Ch R = 1 ,11984.6 ,337.2,337.7,338.2
XS GIS Cut Line= 3
     1693865.951      340583.561     1693969.884      340683.427
     1694067.648      340777.365
#Sta/Elev= 24
       0  792.74    19.2  782.91    28.8  776.78    38.4  771.13      48  766.18
    57.6  761.76    67.3  758.87    76.9  757.43    96.1  756.35   105.7  754.89
   115.3  753.25   124.8  752.04   134.5   751.9   139.8  752.83   144.1  753.59
   153.8  756.56   163.5  758.16   173.2  758.04   192.6   757.5   211.9  757.41
   231.3  757.68   250.7   758.1     270  758.85   279.7  759.32
#Mann= 3 , 0 , 0
       0      .1       0   124.8    .045       0   139.8     .08       0
Bank Sta=124.8,139.8
XS Rating Curve= 0 ,0
Exp/Cntr=0.3,0.1

Type RM Length L Ch R = 1 ,11646.8 ,317.1,327.7,338.4
XS GIS Cut Line= 3
     1693579.305      340769.646     1693695.891       340886.87
     1693894.217      341086.281
#Sta/Elev= 30
       0  863.19     9.7  860.56    29.2  845.78    48.6  830.46    58.4  823.05
    68.1  814.82    77.8   805.4    87.5   798.1   116.7   776.6   126.4  771.95
   136.2  768.68   145.9  761.64   155.6  754.81   165.3  749.39     175   747.3
   200.4  747.53   204.1  747.54   215.4   749.3   223.5  751.07   233.2  752.46
   242.9  752.99   262.3  753.43   281.7  754.42   301.1  755.63   359.3  760.67
   388.4  762.22   417.5  763.06   427.2  763.76   436.9  766.17   446.6  769.31
#Mann= 3 , 0 , 0
       0      .1       0   200.4    .045       0   215.4     .08       0
Bank Sta=200.4,215.4
XS Rating Curve= 0 ,0
Exp/Cntr=0.3,0.1

Type RM Length L Ch R = 1 ,11318.9 ,399.1,380.5,361.9
XS GIS Cut Line= 3
     1693352.231      340800.168     1693438.648      341068.126
     1693506.634      341278.932
#Sta/Elev= 30
       0  879.83    19.4  871.07    38.8  859.73    48.5   859.4      68  844.31
    97.1  819.34   106.8  811.95   116.5  805.63   126.2  803.12   135.9  799.84
   155.3   789.2     165  784.27   184.5  775.13   203.9  766.71   213.6  766.09
   223.3  761.74     233  756.62   242.7  750.96   252.4  746.75   262.1  744.52
     274  743.28   281.6  743.03     289  743.72   320.1  749.55   377.8  751.68
   406.7  752.37   454.9   754.7   474.2  755.22   493.4   756.4     503  758.55
#Mann= 3 , 0 , 0
       0      .1       0     274    .045       0     289     .08       0
Bank Sta=274,289
XS Rating Curve= 0 ,0
Exp/Cntr=0.3,0.1

Type RM Length L Ch R = 1 ,10938.1 ,814.2,826.6,839
XS GIS Cut Line= 3
      1693061.64      341267.922     1693219.229      341343.586
     1693383.077      341422.255
#Sta/Elev= 28
       0  787.09    38.8  771.86    48.6   768.2    58.3  765.58      68  761.54
    77.7  757.98    87.4  753.63    97.1  749.91   106.8  747.63   116.5  746.17
     136  743.49   155.4  740.93     163  740.24   165.1  740.05   174.8  741.42
     178  742.36   184.4  744.25   193.9  746.52   203.5  747.56   232.2  748.97
     280  751.74   289.6  752.24   299.2   752.6   308.7  753.08   318.3  753.68
   337.4  755.37     347  756.36   356.6  757.53
#Mann= 3 , 0 , 0
       0     .06       0     163    .045       0     178     .06       0
Bank Sta=163,178
XS Rating Curve= 0 ,0
Exp/Cntr=0.3,0.1

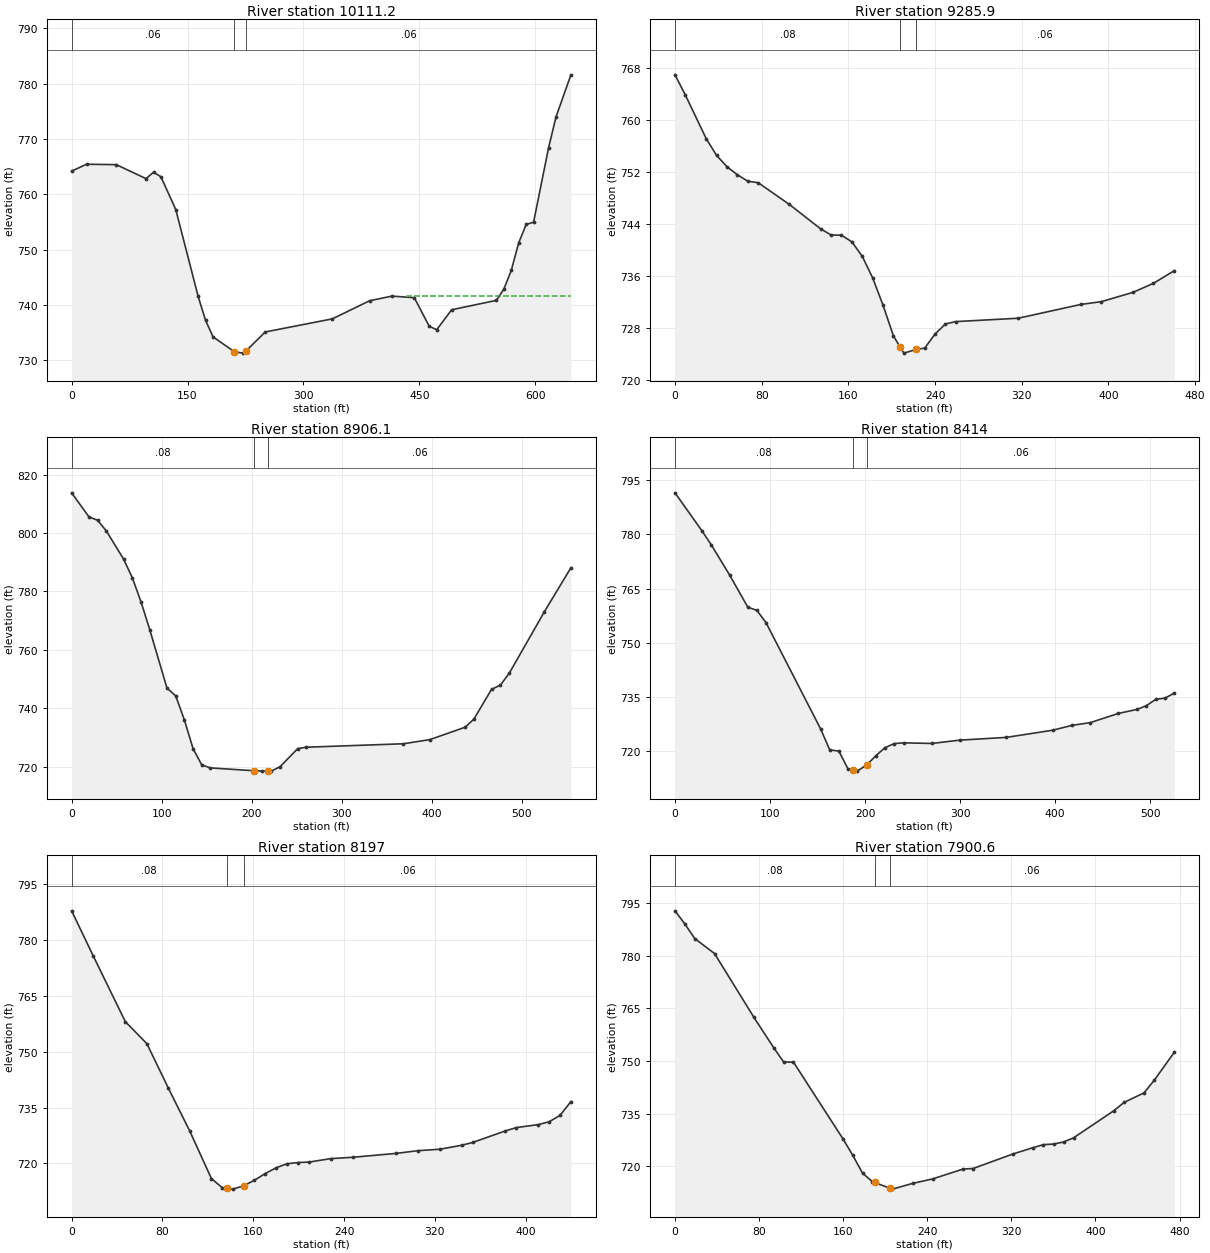
Type RM Length L Ch R = 1 ,10111.2 ,811.6,824.9,838.2
XS GIS Cut Line= 3
     1692458.464      341643.381     1692542.079      341772.828
     1692809.129      342186.254
#Sta/Elev= 30
       0   764.2    19.3  765.44    57.8  765.37    96.3  762.84     106     764
   115.6  763.18   134.8  757.26   163.8  741.56   173.4  737.24   183.1  734.26
   210.7  731.58   221.7  731.33   225.7  731.72   250.6  735.15   337.5  737.52
   385.7  740.79   414.7  741.63   443.6  741.34   462.9  736.18   472.6  735.56
   491.9  739.16   549.8  740.86   559.4  742.86   569.1  746.26   578.7  751.24
   588.4  754.57     598  754.98   617.3  768.35     627  773.98   646.3  781.59
#Mann= 3 , 0 , 0
       0     .06       0   210.7    .045       0   225.7     .06       0
#XS Ineff= 2 , 0
                          433.76          741.62
Permanent Ineff=
       F       F
Bank Sta=210.7,225.7
XS Rating Curve= 0 ,0
Exp/Cntr=0.3,0.1

Type RM Length L Ch R = 1 ,9285.9  ,390.4,379.9,369.5
XS GIS Cut Line= 3
     1691821.017      341685.803     1691818.766      341897.031
     1691816.106      342146.589
#Sta/Elev= 30
       0  766.99     9.6  763.86    28.8  757.15    38.4  754.56      48  752.82
    57.6  751.58    67.2   750.6    76.8  750.36   105.6  747.01   134.4  743.25
     144  742.31   153.6  742.27   163.2  741.26   172.8  739.02   182.4   735.7
     192  731.48   201.6  726.74   207.7  725.06   211.2   724.1   222.7  724.68
   230.4  724.87     240  727.04   249.6   728.6   259.2  728.96   316.8  729.48
   374.4   731.6   393.6  732.04   422.4  733.45   441.6  734.86   460.8  736.81
#Mann= 3 , 0 , 0
       0     .08       0   207.7    .045       0   222.7     .06       0
Bank Sta=207.7,222.7
XS Rating Curve= 0 ,0
Exp/Cntr=0.3,0.1

Type RM Length L Ch R = 1 ,8906.1  ,489.4,491.9,494.5
XS GIS Cut Line= 3
     1691358.837      341782.249      1691451.07       341973.21
     1691600.165      342281.901
#Sta/Elev= 30
       0  813.74    19.3  805.48    28.9  804.34    38.6  800.67    57.8  791.02
    67.5  784.61    77.1  776.42    86.8   766.9     106  746.86   115.7   744.2
   125.3  735.97     135  726.12   144.6  720.57   154.2  719.55   203.2  718.56
   212.1  718.44   218.2  718.45   221.9  718.45   231.7  719.96   251.2  726.15
     261  726.63   368.8  727.81   398.2  729.24   437.3  733.47   447.1  736.26
   466.7  746.45   476.5  747.89   486.3  751.92   525.5  773.07   554.9  788.08
#Mann= 3 , 0 , 0
       0     .08       0   203.2    .045       0   218.2     .06       0
Bank Sta=203.2,218.2
XS Rating Curve= 0 ,0
Exp/Cntr=0.3,0.1

Type RM Length L Ch R = 1 ,8414    ,216.8,217,217.2
XS GIS Cut Line= 3
     1690916.601      341933.097     1690980.654      342113.607
     1691092.279      342428.185
#Sta/Elev= 30
       0  791.49    28.7  780.84    38.3  777.05    57.5  768.73    76.6  759.87
    86.2  758.98    95.8  755.56   153.2   726.2   162.8   720.4   172.4  720.07
     182  715.14   186.8  714.83   191.5  714.53   201.8  716.25   211.2  718.78
     221  721.03   230.8  722.16   240.6  722.35   270.1  722.18   299.5   723.1
   348.6  723.86   397.7  725.86   417.3  727.17     437  727.95   466.4  730.48
   486.1   731.6   495.9  732.62   505.7  734.37   515.5  734.72   525.3   736.1
#Mann= 3 , 0 , 0
       0     .08       0   186.8    .045       0   201.8     .06       0
Bank Sta=186.8,201.8
XS Rating Curve= 0 ,0
Exp/Cntr=0.3,0.1

Type RM Length L Ch R = 1 ,8197    ,292.4,296.3,300.1
XS GIS Cut Line= 3
     1690722.637      342017.417     1690775.337      342169.491
     1690866.642      342432.962
#Sta/Elev= 30
       0  787.76    18.9  775.75    47.3  758.03    66.3  752.12    85.2   740.2
   104.1  728.66   123.1  715.96   132.5  713.52   136.6  713.34     142  713.11
   151.6  714.01     161  715.49   170.6   717.3   180.2  718.85   189.8  719.92
   199.4  720.24     209  720.36   228.2  721.29   247.5  721.65     286   722.7
   305.2  723.43   324.4  723.81   343.6  724.88   353.2  725.62   382.1  728.73
   391.7  729.62   410.9  730.41   420.6  731.17   430.2  732.88   439.8  736.59
#Mann= 3 , 0 , 0
       0     .08       0   136.6    .045       0   151.6     .06       0
Bank Sta=136.6,151.6
XS Rating Curve= 0 ,0
Exp/Cntr=0.3,0.1

Type RM Length L Ch R = 1 ,7900.6  ,620.6,623,625.4
XS GIS Cut Line= 3
     1690455.544      342023.696     1690486.281      342208.944
     1690533.289      342492.258
#Sta/Elev= 30
       0  792.86     9.4   789.1    18.8  784.95    37.6  780.67    75.1  762.45
    93.9   753.8   103.3  749.74   112.7  749.68   159.6  727.89     169  723.17
   178.4  718.01   187.8  715.59   189.8  715.36   204.8  713.69   206.9  713.46
   226.1   715.1   245.2  716.38   273.9  719.18   283.5  719.34   321.8  723.52
     341  725.33   350.5  726.15   360.1  726.32   369.7  726.91   379.2  728.11
   417.5  735.83   427.1  738.18   446.2  740.92   455.8  744.47     475   752.5
#Mann= 3 , 0 , 0
       0     .08       0   189.8    .045       0   204.8     .06       0
Bank Sta=189.8,204.8
XS Rating Curve= 0 ,0
Exp/Cntr=0.3,0.1

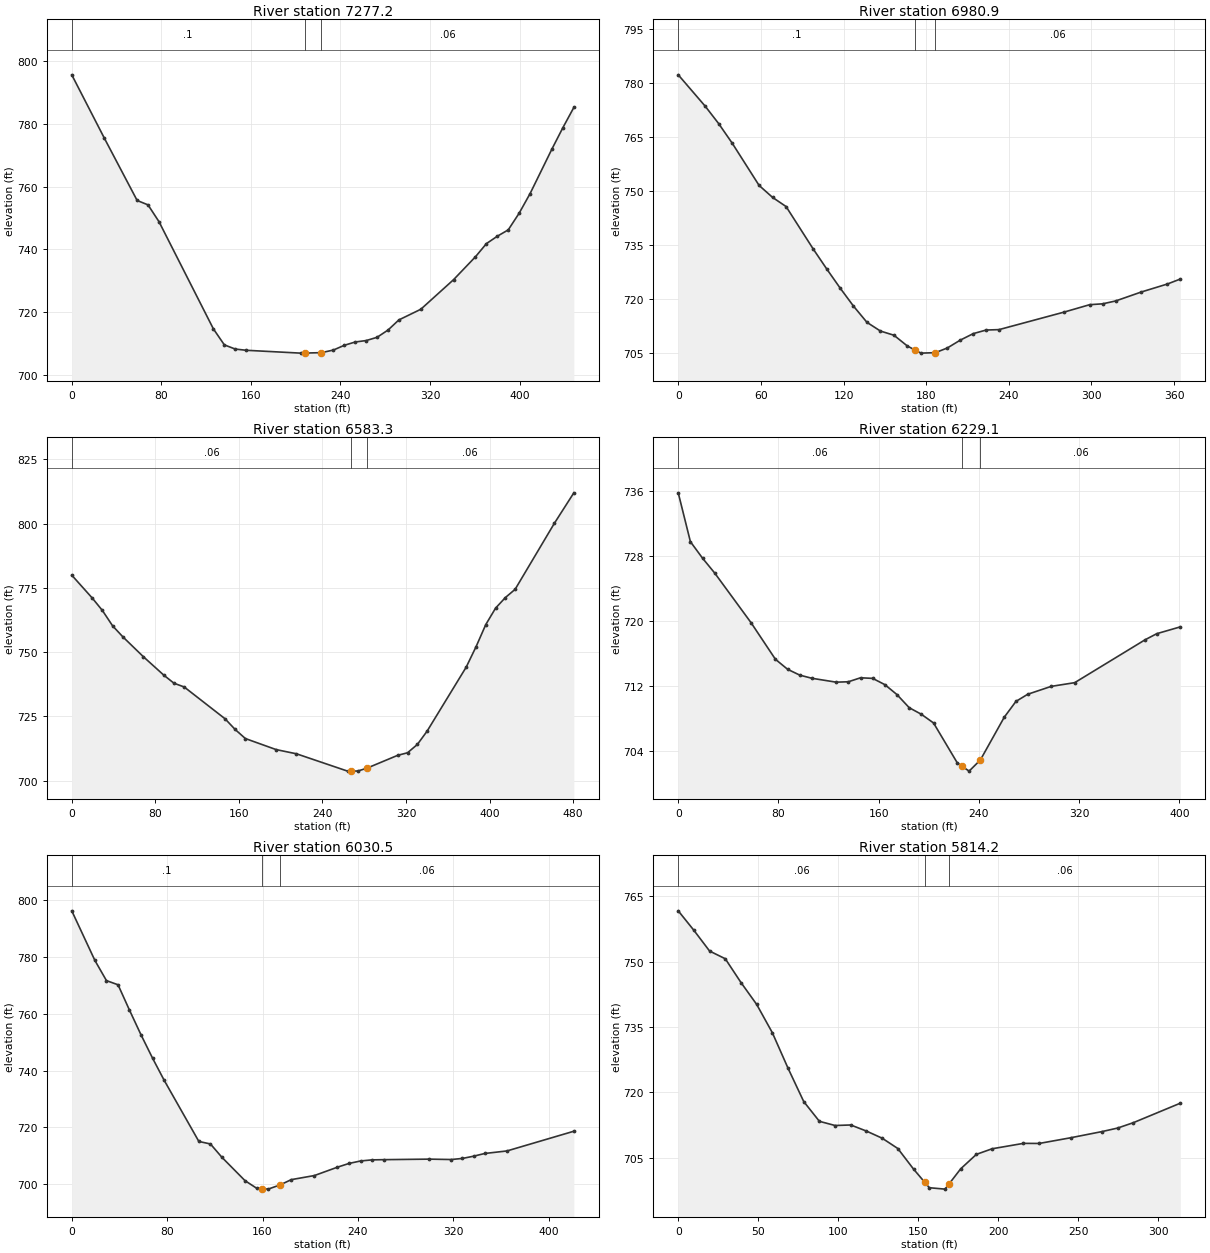
Type RM Length L Ch R = 1 ,7277.2  ,296.3,296.3,296.4
XS GIS Cut Line= 3
     1689855.039      342025.503     1689867.348      342239.298
     1689880.816       342473.22
#Sta/Elev= 30
       0  795.67    29.2   775.4    58.4   755.6    68.1   754.2    77.9  748.85
   126.5  714.66   136.3  709.55     146  708.22   155.7  707.83   204.4  706.92
     208  706.94     223  707.07   233.7   707.9   243.4  709.41   253.2  710.47
     263  710.93   272.7  711.96   282.5  714.28   292.2  717.51   311.8  720.91
   341.1  730.36   360.6  737.64   370.4  741.84   380.1  744.19   389.9  746.23
   399.6  751.52   409.4  757.79   428.9  771.99   438.7  778.81   448.5  785.27
#Mann= 3 , 0 , 0
       0      .1       0     208    .045       0     223     .06       0
Bank Sta=208,223
XS Rating Curve= 0 ,0
Exp/Cntr=0.3,0.1

Type RM Length L Ch R = 1 ,6980.9  ,377.9,397.5,417.1
XS GIS Cut Line= 3
     1689561.792      342080.702     1689572.231       342266.37
     1689582.251      342444.601
#Sta/Elev= 30
       0  782.23    19.6  773.51    29.4  768.66    39.2  763.24    58.7  751.52
    68.5  748.19    78.3  745.65    97.9  733.92   107.7  728.38   117.4  723.09
   127.2  718.02     137   713.5   146.8  711.08   156.6  709.92   166.4  706.91
   171.7  705.85   176.2  704.95   186.7  705.08   195.4  706.39   204.8  708.57
   214.2  710.37   223.5  711.36   232.9  711.48   279.9  716.32   298.7   718.4
   308.1  718.64   317.5  719.43   336.3  721.94   355.1  724.14   364.5  725.52
#Mann= 3 , 0 , 0
       0      .1       0   171.7    .045       0   186.7     .06       0
Bank Sta=171.7,186.7
XS Rating Curve= 0 ,0
Exp/Cntr=0.3,0.1

Type RM Length L Ch R = 1 ,6583.3  ,354.7,354,353.3
XS GIS Cut Line= 3
     1689401.661      341979.999     1689189.845      342182.902
     1689054.593      342312.464
#Sta/Elev= 30
       0  779.92    19.6  771.02    29.3  766.19    39.1   760.2    48.9  755.93
    68.4  748.25      88  741.06    97.8  737.89   107.6  736.43   146.7  724.06
   156.4  719.89   166.2  716.36   195.6  712.07   215.1  710.43     264  703.69
   267.3   703.7   273.8  703.73   282.3   704.8     312  709.84   321.4  710.83
   330.8  714.06   340.1  719.22   377.6  744.17     387  752.09   396.3   760.7
   405.7  767.11   415.1  771.22   424.4  774.42   461.9  800.06   480.6  811.95
#Mann= 3 , 0 , 0
       0     .06       0   267.3    .045       0   282.3     .06       0
Bank Sta=267.3,282.3
XS Rating Curve= 0 ,0
Exp/Cntr=0.3,0.1

Type RM Length L Ch R = 1 ,6229.1  ,221.8,198.6,175.4
XS GIS Cut Line= 3
     1689163.484      341730.179     1689009.336      341877.841
     1688874.083      342007.403
#Sta/Elev= 30
       0  735.79     9.7  729.77    19.4  727.73    29.1   725.9    58.2  719.76
    77.6  715.26    87.3  714.03      97  713.31   106.7  712.92   126.1  712.44
   135.8  712.49   145.5  712.98   155.2  712.91     165  712.13   174.6  710.91
   184.4  709.29   194.1  708.48   203.8  707.41   222.8  702.48   226.2  702.11
   232.2  701.47   241.2  702.85   260.3  708.13   269.6  710.07     279  710.95
   297.7  711.92   316.5  712.38   372.7  717.67     382  718.42   400.8  719.26
#Mann= 3 , 0 , 0
       0     .06       0   226.2    .045       0   241.2     .06       0
Bank Sta=226.2,241.2
XS Rating Curve= 0 ,0
Exp/Cntr=0.3,0.1

Type RM Length L Ch R = 1 ,6030.5  ,224,216.3,208.6
XS GIS Cut Line= 3
     1688843.511      341586.931     1688904.136      341861.281
     1688861.909      341994.897
#Sta/Elev= 30
       0  796.21    19.4  778.74    29.1  771.64    38.8  770.18    48.4  761.26
    58.1  752.54    67.8  744.31    77.5  736.55   106.6  715.02   116.3  714.14
     126  709.41   145.3  701.22     155  698.57   159.8  698.41   164.7  698.24
   174.8  699.74   184.1  701.58   203.5  703.02   222.8  705.96   232.5  707.28
   242.2  708.15   251.9  708.54   261.6  708.61   299.6   708.8   318.3  708.66
   327.7  709.05     337  709.83   346.4  710.79     365  711.68   421.1  718.62
#Mann= 3 , 0 , 0
       0      .1       0   159.8    .045       0   174.8     .06       0
Bank Sta=159.8,174.8
XS Rating Curve= 0 ,0
Exp/Cntr=0.3,0.1

Type RM Length L Ch R = 1 ,5814.2  ,191.9,213.2,234.5
XS GIS Cut Line= 2
     1688618.218      341736.297     1688784.036      342002.606
#Sta/Elev= 30
       0  761.66     9.8  757.18    19.6  752.43    29.4  750.66    39.2  745.21
      49  740.19    58.8  733.69    68.6  725.55    78.4   717.9    88.2  713.36
      98   712.4   107.8  712.52   117.6  711.12   127.4  709.49   137.2  707.12
     147  702.41   154.1  699.33   156.9  698.12   166.7   697.8   169.1  698.94
   176.5  702.47   186.3  705.78   196.1  707.06   215.7   708.3   225.5  708.28
   245.1  709.58   264.7     711   274.5  711.81   284.3  713.04   313.7  717.52
#Mann= 3 , 0 , 0
       0     .06       0   154.1    .045       0   169.1     .06       0
Bank Sta=154.1,169.1
XS Rating Curve= 0 ,0
Exp/Cntr=0.3,0.1

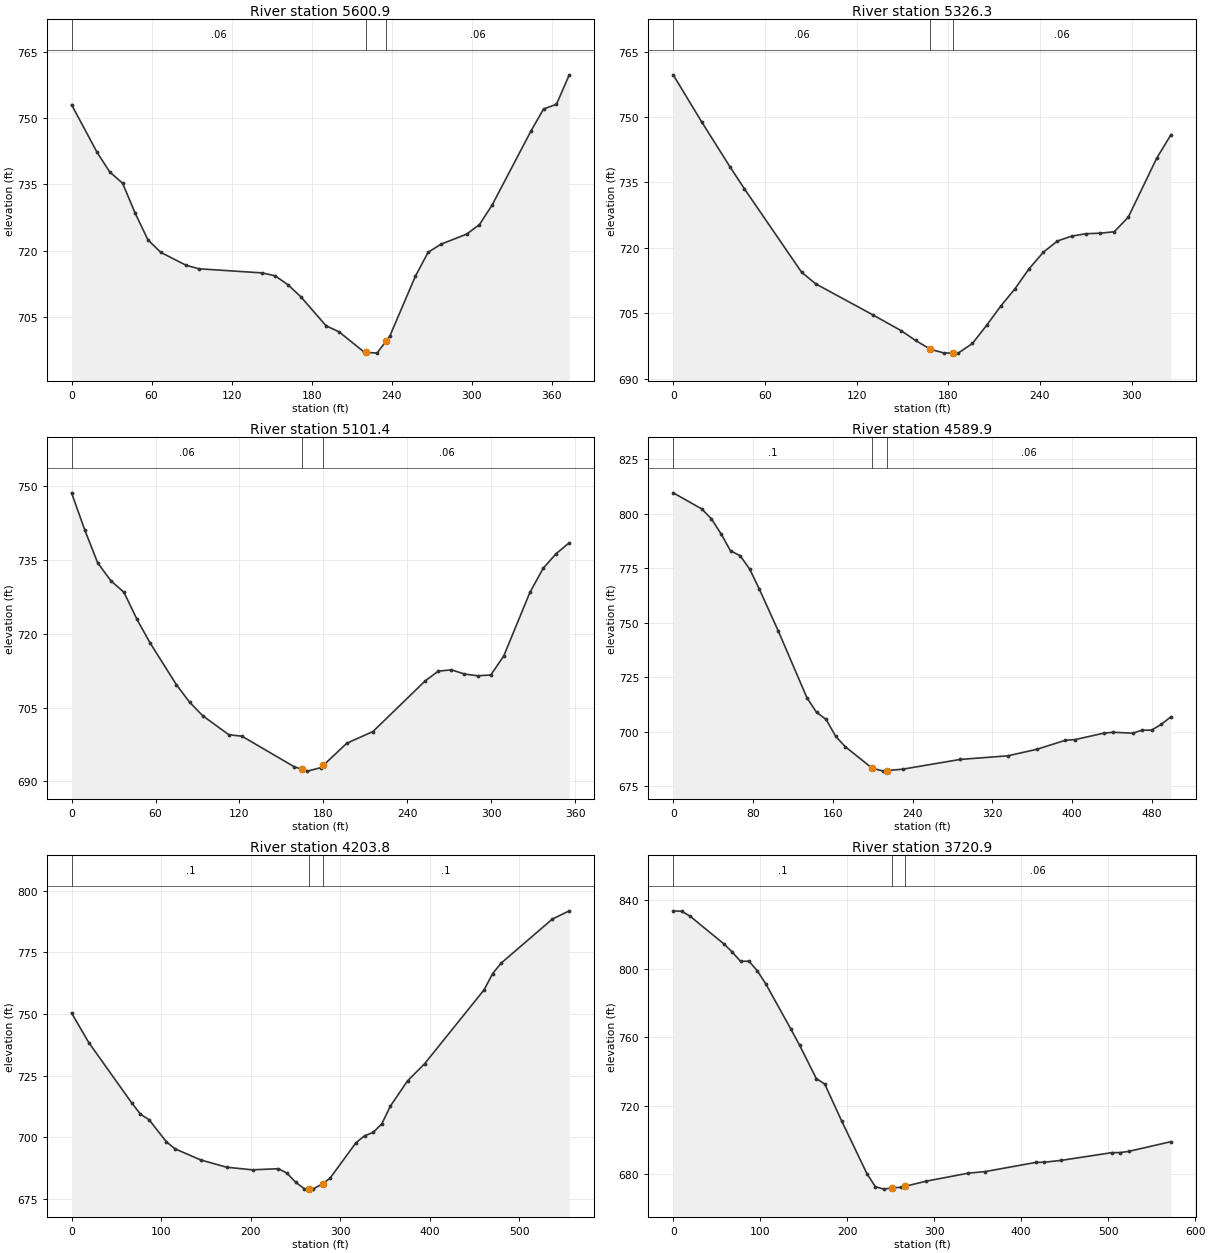
Type RM Length L Ch R = 1 ,5600.9  ,267.5,274.5,281.7
XS GIS Cut Line= 3
     1688589.089      341727.429     1688499.519      341958.679
     1688454.382      342075.215
#Sta/Elev= 30
       0  753.04    19.1  742.26    28.6   737.8    38.2  735.26    47.7  728.45
    57.2  722.44    66.8  719.59    85.8  716.66    95.4  715.86   143.1  714.92
   152.6  714.26   162.2  712.24   171.7  709.56   190.8  702.93   200.3  701.61
   219.4  696.97   220.8  696.94   228.9  696.75   235.8   699.5   238.4  700.53
   257.6  714.12   267.2  719.59   276.8  721.42   296.1  723.71   305.7  725.87
   315.3  730.36   344.1  746.97   353.7  752.05   363.4  753.12     373   759.8
#Mann= 3 , 0 , 0
       0     .06       0   220.8    .045       0   235.8     .06       0
Bank Sta=220.8,235.8
XS Rating Curve= 0 ,0
Exp/Cntr=0.3,0.1

Type RM Length L Ch R = 1 ,5326.3  ,229.5,224.8,219.9
XS GIS Cut Line= 3
     1688468.315      341596.521     1688356.907      341734.344
     1688263.575      341849.805
#Sta/Elev= 27
       0  759.69    18.6  748.91    37.3   738.5    46.6  733.54      84   714.4
    93.3  711.72   130.6  704.62   149.2  700.98   158.6  698.73   168.3  696.73
   177.2  695.85   183.3  695.84   186.5  695.83   195.8  698.05   205.1  702.22
   214.3   706.6   223.6  710.58   232.9   715.2   242.2  718.98   251.4  721.56
   260.7  722.67     270  723.23   279.3  723.35   288.6  723.68   297.8  727.04
   316.4  740.56   325.7  745.94
#Mann= 3 , 0 , 0
       0     .06       0   168.3    .045       0   183.3     .06       0
Bank Sta=168.3,183.3
XS Rating Curve= 0 ,0
Exp/Cntr=0.3,0.1

Type RM Length L Ch R = 1 ,5101.4  ,526.3,511.3,496.4
XS GIS Cut Line= 3
     1688249.923      341464.665     1688163.001       341630.59
     1688084.869      341779.734
#Sta/Elev= 30
       0  748.65     9.4  741.14    18.7   734.4    28.1  730.78    37.5  728.42
    46.8  722.91    56.2   718.1    74.9  709.67    84.3  706.11    93.7  703.35
   112.4  699.48   121.8  699.18   159.2  692.96     165  692.42   168.6  692.08
     178  692.78     180  693.27   196.7  697.75   215.4  700.13   252.8  710.44
   262.1   712.4   271.5  712.67   280.8  711.82   290.2  711.46   299.6  711.62
   308.9   715.5   327.6  728.42     337  733.29   346.3  736.28   355.7   738.5
#Mann= 3 , 0 , 0
       0     .06       0     165    .045       0     180     .06       0
Bank Sta=165,180
XS Rating Curve= 0 ,0
Exp/Cntr=0.3,0.1

Type RM Length L Ch R = 1 ,4589.9  ,366,386.4,406.7
XS GIS Cut Line= 3
     1687669.854       341229.77     1687720.034      341483.536
     1687766.643      341719.244
#Sta/Elev= 30
       0  809.67    28.7  802.26    38.3  797.72    47.9   790.9    57.5     783
    67.1  780.81    76.6  774.69    86.2   765.6   105.4  746.17   134.1  715.52
   143.7  708.85   153.3  705.59   162.9  697.83   172.4  693.12   199.3  683.24
   210.8  681.84   214.3  682.12   229.9  682.72   287.5   687.2   335.6  688.88
   364.4  691.85   393.2  696.01   402.8  696.32   431.7  699.28   441.3  699.69
   460.5  699.27   470.1  700.62   479.7  700.69   489.3  703.32     499  706.81
#Mann= 3 , 0 , 0
       0      .1       0   199.3    .045       0   214.3     .06       0
Bank Sta=199.3,214.3
XS Rating Curve= 0 ,0
Exp/Cntr=0.3,0.1

Type RM Length L Ch R = 1 ,4203.8  ,488.7,482.3,475.9
XS GIS Cut Line= 3
     1687605.205       341302.34     1687359.846      341573.715
     1687232.315      341714.768
#Sta/Elev= 30
       0  750.45    19.3  738.43    67.4  713.91      77  709.44    86.6  707.18
   105.9  698.26   115.5  695.41   144.4  690.86   173.3  687.93   202.2  686.87
   231.1  687.33   240.7  685.52   250.3  681.84     260  679.25   265.8  679.13
   269.6  679.05   280.8  681.31   288.8   683.5   317.7  697.84   327.3  700.66
     337  702.05   346.6  705.54   356.2  712.73   375.4  722.97   394.4  729.87
   460.9  759.86   470.4  766.42   479.9  770.65     537  788.48     556  791.85
#Mann= 3 , 0 , 0
       0      .1       0   265.8    .045       0   280.8      .1       0
Bank Sta=265.8,280.8
XS Rating Curve= 0 ,0
Exp/Cntr=0.3,0.1

Type RM Length L Ch R = 1 ,3720.9  ,411.5,401.5,391.6
XS GIS Cut Line= 3
     1687386.696      340874.479     1687315.086       341022.58
     1687137.629      341389.589
#Sta/Elev= 30
       0  833.88     9.7  833.61    19.4  830.76    58.1  814.64    67.7  809.92
    77.4  804.36    87.1   804.5    96.8  798.78   106.4  791.23   135.5  764.62
   145.2  755.51   164.5  735.95   174.2  732.74   193.6  711.25   222.7  680.41
   232.4  672.79   242.2  671.37   251.5  672.16   261.6   672.4   266.5     673
   290.7  676.01   339.2  680.68   358.6  681.61   416.9  686.98   426.6  687.08
     446  688.15   504.2  692.68   513.9  692.71   523.6  693.41   572.2  699.08
#Mann= 3 , 0 , 0
       0      .1       0   251.5    .045       0   266.5     .06       0
Bank Sta=251.5,266.5
XS Rating Curve= 0 ,0
Exp/Cntr=0.3,0.1

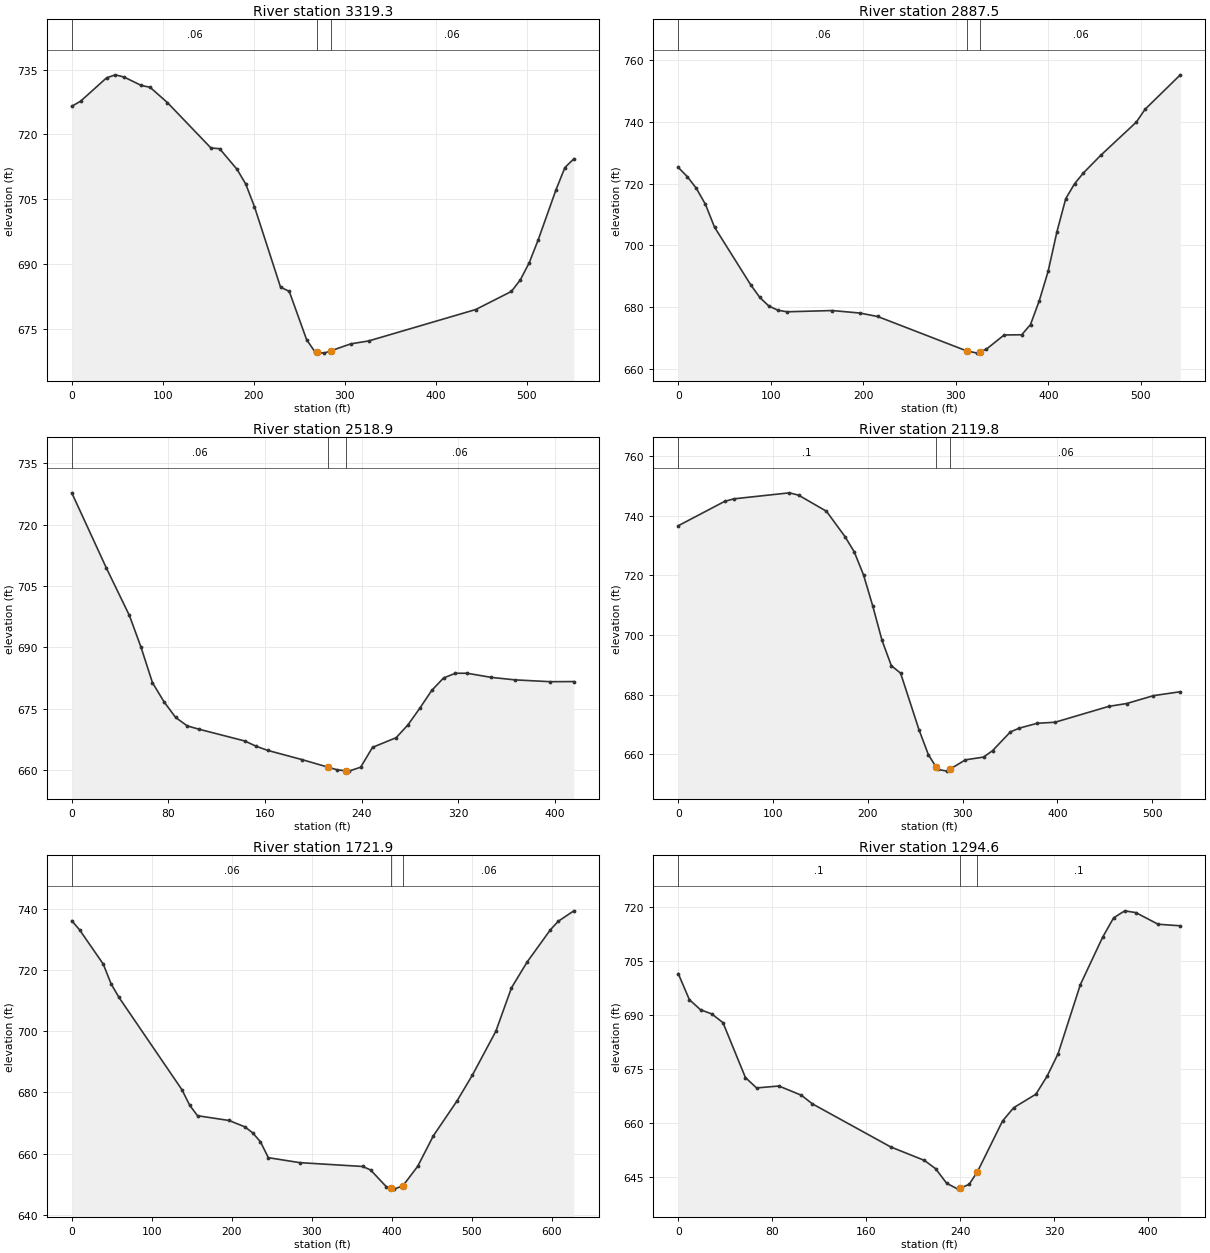
Type RM Length L Ch R = 1 ,3319.3  ,402,431.6,461.1
XS GIS Cut Line= 3
     1686889.962      340762.419     1686887.747      341039.505
     1686885.553      341313.897
#Sta/Elev= 30
       0  726.54     9.6  727.69    38.2  733.11    47.8  733.81    57.3  733.31
    76.4  731.35      86  730.93   105.1  727.38   152.9  716.87   162.4  716.72
   181.6  711.92   191.1  708.53   200.7  703.28   229.3  684.68   238.9  683.69
     258  672.49   267.5   669.6   269.5  669.56   277.1   669.4   284.5  669.93
   306.5  671.55   326.1  672.22   443.7  679.49   482.9  683.68   492.7  686.35
   502.5  690.33   512.3  695.59   531.9  707.21   541.7  712.36   551.5  714.37
#Mann= 3 , 0 , 0
       0     .06       0   269.5    .045       0   284.5     .06       0
Bank Sta=269.5,284.5
XS Rating Curve= 0 ,0
Exp/Cntr=0.3,0.1

Type RM Length L Ch R = 1 ,2887.5  ,369.3,368.6,367.9
XS GIS Cut Line= 3
     1686859.184      340805.225     1686537.494      340891.696
     1686335.218      340946.068
#Sta/Elev= 30
       0  725.22     9.8  722.24    19.6  718.44    29.4  713.28    39.2  705.92
    78.4  687.24    88.2  683.18      98   680.4   107.8  679.06   117.6  678.56
   166.6  678.96     196  678.16   215.5  677.04   311.6  665.93   323.3   665.2
   326.6  665.64   333.1   666.5   352.2  671.07   371.2  671.13   380.7  674.44
   390.2  682.15   399.8  691.69   409.3  704.47   418.8  715.12   428.3  719.92
   437.8   723.4   456.9  729.21     495  739.83   504.5  743.99   542.6  755.13
#Mann= 3 , 0 , 0
       0     .06       0   311.6    .045       0   326.6     .06       0
Bank Sta=311.6,326.6
XS Rating Curve= 0 ,0
Exp/Cntr=0.3,0.1

Type RM Length L Ch R = 1 ,2518.9  ,427.2,399.2,371.2
XS GIS Cut Line= 3
     1686657.792       340472.56     1686447.682      340536.296
      1686259.98      340593.235
#Sta/Elev= 30
       0  727.74    28.6  709.41    47.7   697.8    57.3  690.07    66.8  681.39
    76.4   676.7    85.9  672.92    95.5  670.84     105  670.04   143.2  667.15
   152.7  665.85   162.3  664.84   190.9  662.57   212.1  660.75   219.6  660.11
   227.1  659.86   229.4  659.78   239.2  660.74     249  665.58   268.6  667.95
   278.4   671.1   288.2  675.16     298  679.47   307.8  682.52   317.6  683.68
   327.4  683.68   347.1  682.68   366.7  682.07   396.1  681.62   415.7  681.65
#Mann= 3 , 0 , 0
       0     .06       0   212.1    .045       0   227.1     .06       0
Bank Sta=212.1,227.1
XS Rating Curve= 0 ,0
Exp/Cntr=0.3,0.1

Type RM Length L Ch R = 1 ,2119.8  ,374.3,397.7,421.1
XS GIS Cut Line= 3
     1686154.264      340082.324     1686140.102      340394.739
     1686130.278      340611.446
#Sta/Elev= 30
       0  736.69    48.9  744.86    58.6  745.72   117.3  747.74     127  746.95
   156.4  741.55   175.9  733.06   185.7  727.94   195.5  720.17   205.2  709.79
     215  698.23   224.8  689.75   234.6  687.21   254.1  668.14   263.9  659.87
   272.2  655.65   273.6  654.94   283.4  654.34   287.2   655.1     303  658.13
   322.2  659.06   331.6  661.21   350.5  667.52   359.9  668.77   378.8   670.4
   397.6  670.75   454.2  676.07   473.1  677.03   501.4  679.67   529.7  680.99
#Mann= 3 , 0 , 0
       0      .1       0   272.2    .045       0   287.2     .06       0
Bank Sta=272.2,287.2
XS Rating Curve= 0 ,0
Exp/Cntr=0.3,0.1

Type RM Length L Ch R = 1 ,1721.9  ,405.2,427.2,449.1
XS GIS Cut Line= 3
     1686134.413      340090.411     1685744.078       340298.33
     1685580.486       340385.47
#Sta/Elev= 30
       0  736.13     9.8  733.14    39.3  721.98    49.1  715.52      59  711.06
   137.6  680.91   147.4  675.79   157.2  672.36   196.6   670.8   216.2  668.74
     226   666.8   235.9  663.82   245.7  658.64     285  657.01   363.6  655.76
   373.5  654.63   393.1  649.16     399  648.68     403  648.35     414  649.47
   432.4  655.81     452   665.8   481.3  677.09   500.8  685.65   530.1  699.98
   549.6  714.17   569.1  722.59   598.3  733.18   608.1  735.95   627.6  739.37
#Mann= 3 , 0 , 0
       0     .06       0     399    .045       0     414     .06       0
Bank Sta=399,414
XS Rating Curve= 0 ,0
Exp/Cntr=0.3,0.1

Type RM Length L Ch R = 1 ,1294.6  ,387.1,375.4,363.7
XS GIS Cut Line= 3
     1686079.958      339990.411     1685851.929      339871.432
     1685700.948      339792.653
#Sta/Elev= 30
       0  701.45     9.5  694.21      19  691.42    28.6  690.26    38.1  687.84
    57.2  672.62    66.7  669.74    85.7  670.27   104.8  667.72   114.3  665.31
     181  653.36   209.6  649.64   219.1  647.35   228.6  643.28   238.2  641.67
   239.8  641.89   247.7     643   254.8  646.51   276.1  660.55   285.6  664.25
   304.5  667.99     314  672.95   323.4   679.2   342.4   698.4   361.3   711.5
   370.7  716.91   380.2  718.86   389.7  718.36   408.6  715.14   427.5  714.71
#Mann= 3 , 0 , 0
       0      .1       0   239.8    .045       0   254.8      .1       0
Bank Sta=239.8,254.8
XS Rating Curve= 0 ,0
Exp/Cntr=0.3,0.1

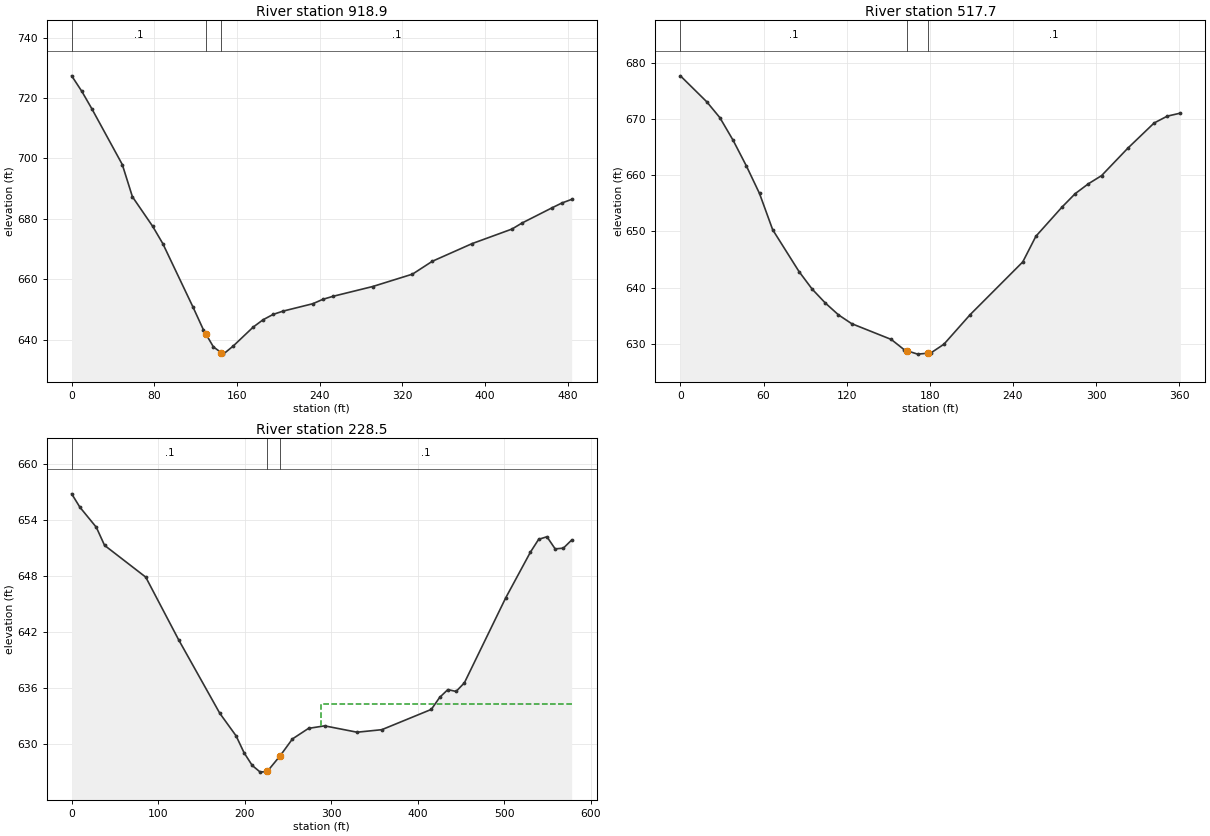
Type RM Length L Ch R = 1 ,918.9   ,409.4,401.3,393.1
XS GIS Cut Line= 3
     1686183.084      339554.471     1686046.025      339559.547
     1685699.385      339572.385
#Sta/Elev= 30
       0  727.35     9.8  722.23    19.6   716.4      49  697.98    58.8  687.31
    78.4  677.52    88.2   671.8   117.6  650.66   127.4  643.34   129.7  641.99
   137.2  637.58   144.7  635.71   146.8  635.19   156.4  637.88   175.7  644.14
   185.3  646.58     195  648.34   204.6  649.43   233.5  651.89   243.1  653.33
   252.8  654.32   291.3  657.57   329.9  661.68   349.1  665.94   387.7   671.8
   426.2  676.61   435.8  678.58   464.8  683.61   474.4  685.22     484  686.44
#Mann= 3 , 0 , 0
       0      .1       0   129.7    .045       0   144.7      .1       0
Bank Sta=129.7,144.7
XS Rating Curve= 0 ,0
Exp/Cntr=0.3,0.1

Type RM Length L Ch R = 1 ,517.7   ,292.8,289,285.1
XS GIS Cut Line= 3
     1686046.953      339136.176     1685888.999      339202.171
     1685713.945      339275.309
#Sta/Elev= 30
       0  677.66      19  673.05    28.5  670.22      38  666.22    47.6  661.65
    57.1  656.74    66.6   650.3    85.6  642.87    95.1  639.74   104.6  637.27
   114.1  635.16   123.6   633.6   152.2  630.79   161.7  628.93   163.6  628.78
   171.2  628.18   178.6  628.34   180.7  628.38   190.2  629.94   209.1  635.19
   247.1  644.57   256.6  649.14   275.5  654.34     285  656.72   294.5  658.47
     304  659.92     323  664.81   341.9  669.27   351.4  670.49   360.9  671.03
#Mann= 3 , 0 , 0
       0      .1       0   163.6    .045       0   178.6      .1       0
Bank Sta=163.6,178.6
XS Rating Curve= 0 ,0
Exp/Cntr=0.3,0.1

Type RM Length L Ch R = 1 ,228.5   ,234.9,228.4,221.9
XS GIS Cut Line= 4
     1685964.083      338946.598     1685784.054      338931.336
     1685666.592      339006.707     1685461.357      339162.282
#Sta/Elev= 30
       0  656.81     9.5  655.38    28.5  653.23      38   651.3    85.6   647.9
   123.6   641.2   171.2  633.33     190  630.92   199.3   629.1   208.6  627.76
   217.9  627.04   226.1  627.12   241.1  628.81   255.1  630.59   273.7  631.72
   292.3  631.99   329.8  631.31   358.4  631.58   415.6  633.75   425.2  635.03
   434.7  635.87   444.2  635.67   453.8  636.59   501.5  645.67   530.1  650.57
   539.6  651.94   549.2  652.22   558.7  650.92   568.2     651   577.8  651.87
#Mann= 3 , 0 , 0
       0      .1       0   226.1    .045       0   241.1      .1       0
#XS Ineff= 2 , 0
                          287.86          634.35
Permanent Ineff=
       F       F
Bank Sta=226.1,241.1
XS Rating Curve= 0 ,0
Exp/Cntr=0.3,0.1

Chan Stop Cuts=-1
Use User Specified Reach Order=0
Composite Channel Slope=5